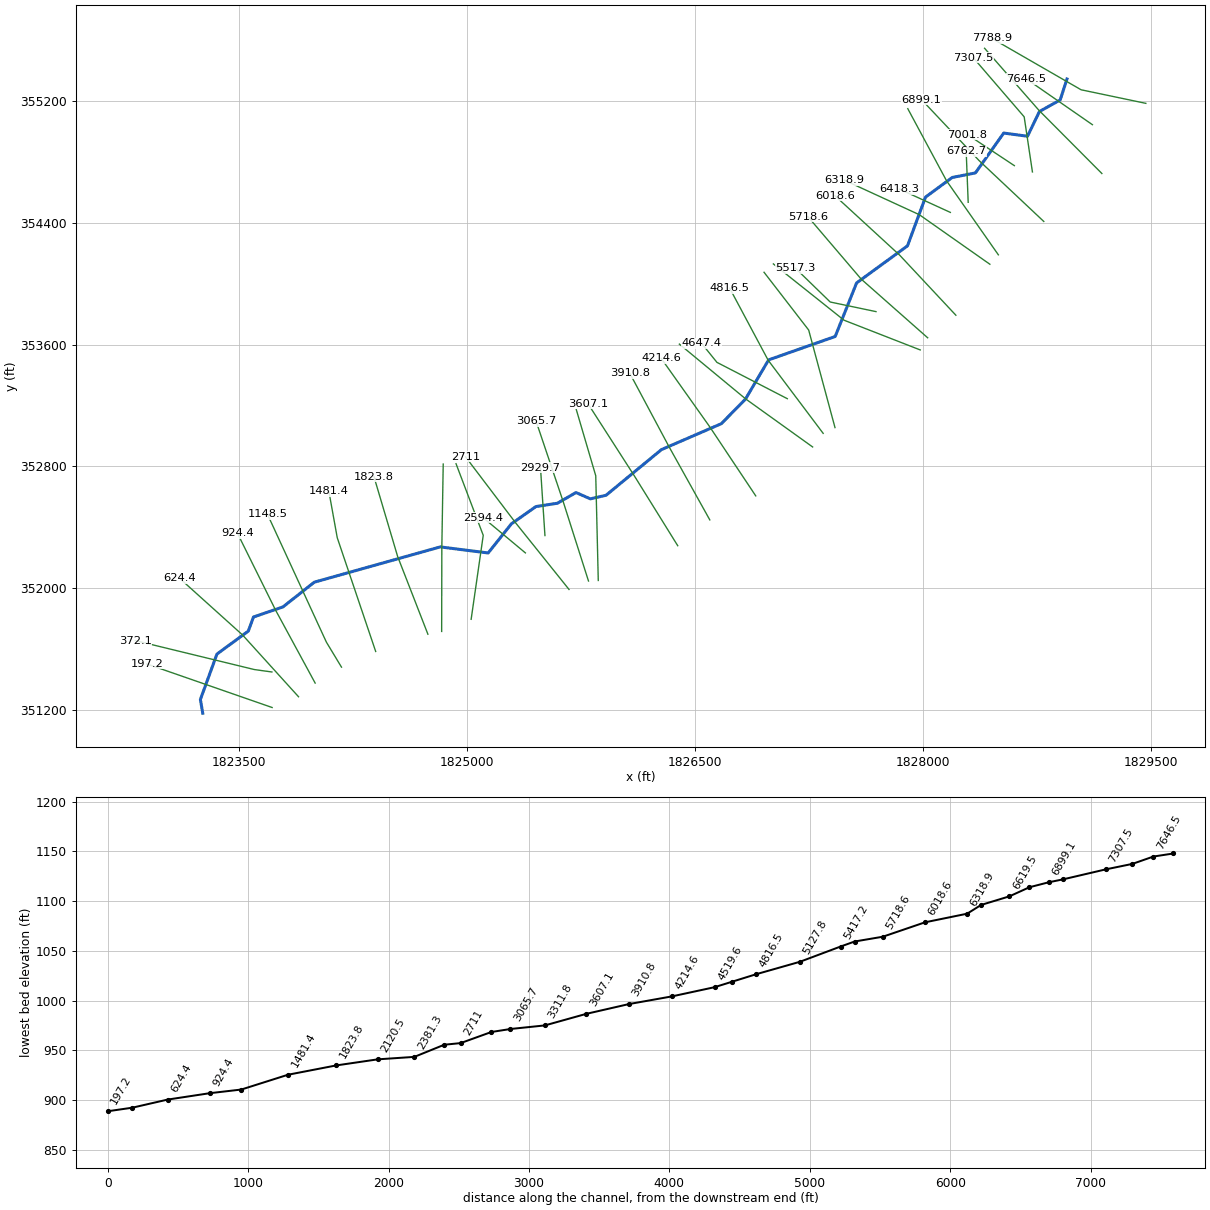
--- RckhsCrk2.prj (project) ---

Proj Title=RckhsCrk2
Current Plan=p01
Default Exp/Contr=0,0
English Units
Geom File=g01
Flow File=f01
Plan File=p01
BEGIN DESCRIPTION:
END DESCRIPTION:
DSS Export Rating Curves= 0
DSS Export Rating Curve Sorted= 0
DSS Export Volume Flow Curves= 0
DXF OffsetX= 0
DXF OffsetY= 0
DXF ScaleX= 0
DXF ScaleY= 0

--- RckhsCrk2.p01 (plan) ---

Plan Title=Floodplain
Program Version=4.00
Geom File=g01
Flow File=f01
K Sum by GR=0
Std Step Tol=0.01
Critical Tol=0.01
Num of Std Step Trials=20
Max Error Tol=0.3
Flow Tol Ratio=0.001
Split Flow NTrial=30
Split Flow Tol=0.02
Split Flow Ratio=0.02
Log Output Level=0
Friction Slope Method=1
Unsteady Friction Slope Method=2
Unsteady Bridges Friction Slope Method=1
Global Log Level=0
CheckData=False
Run HTab=0
Run UNet=0
Run PostProcess=0
UNET Theta=0
UNET Theta Warmup=0
UNET ZTol=0
UNET ZSATol=0
UNET MxIter=0
UNET MaxInSteps=0
UNET DtIC=0
UNET DtMin=0
UNET MaxCRTS=0
UNET WFStab=0
UNET SFStab=0
UNET WFX=0
UNET SFX=0
UNET DSS MLevel=0
UNET DZMax Abort=0
UNET Convert EG Bridges=0
UNET Use Existing IB Tables=0
UNET Froude Limit=0
UNET Froude Power=0
Write IC File=0
Echo Input=False
Echo Output=False
Write Detailed=0

--- RckhsCrk2.f01 (steady flow) ---

Flow Title=NFF Regression Equation
Program Version=4.00
Number of Profiles=1
Profile Names=P100yr
River Rch & RM=RckhsCrk2,Main      ,7788.9
861.5325
River Rch & RM=RckhsCrk2,Main      ,7001.8
894.6682
River Rch & RM=RckhsCrk2,Main      ,4816.5
990.7291
River Rch & RM=RckhsCrk2,Main      ,2929.7
1068.822
River Rch & RM=RckhsCrk2,Main      ,197.2
1178.452
Boundary for River Rch & Prof#=RckhsCrk2,Main      ,1
Up Type=0
Dn Type=3
Dn Slope=0.025375

--- RckhsCrk2.g01 (geometry) ---

Geom Title=USGS 3m DEM
Program Version=4.10

River Reach=RckhsCrk2       ,Main
Reach XY= 30
     1828946.901      355344.301     1828902.319       355206.81
     1828765.889      355130.988     1828687.403       354968.46
     1828531.105      354989.303     1828344.863      354727.539
     1828192.451      354697.554     1828016.612      354568.613
     1827898.078      354248.204     1827563.333      354004.647
     1827422.655      353652.979     1826985.016      353499.297
     1826832.618      353241.408     1826674.335      353080.285
     1826279.977      352909.612     1825915.652      352609.725
     1825812.754      352586.283     1825718.076      352627.785
     1825596.541      352557.634     1825454.569      352535.495
     1825293.434      352422.159     1825140.662      352230.722
     1824825.393      352270.536     1823997.257      352038.796
     1823791.277      351876.481     1823597.205      351810.059
     1823563.338      351717.584     1823357.004      351566.566
     1823248.125      351268.234      1823263.76      351177.978

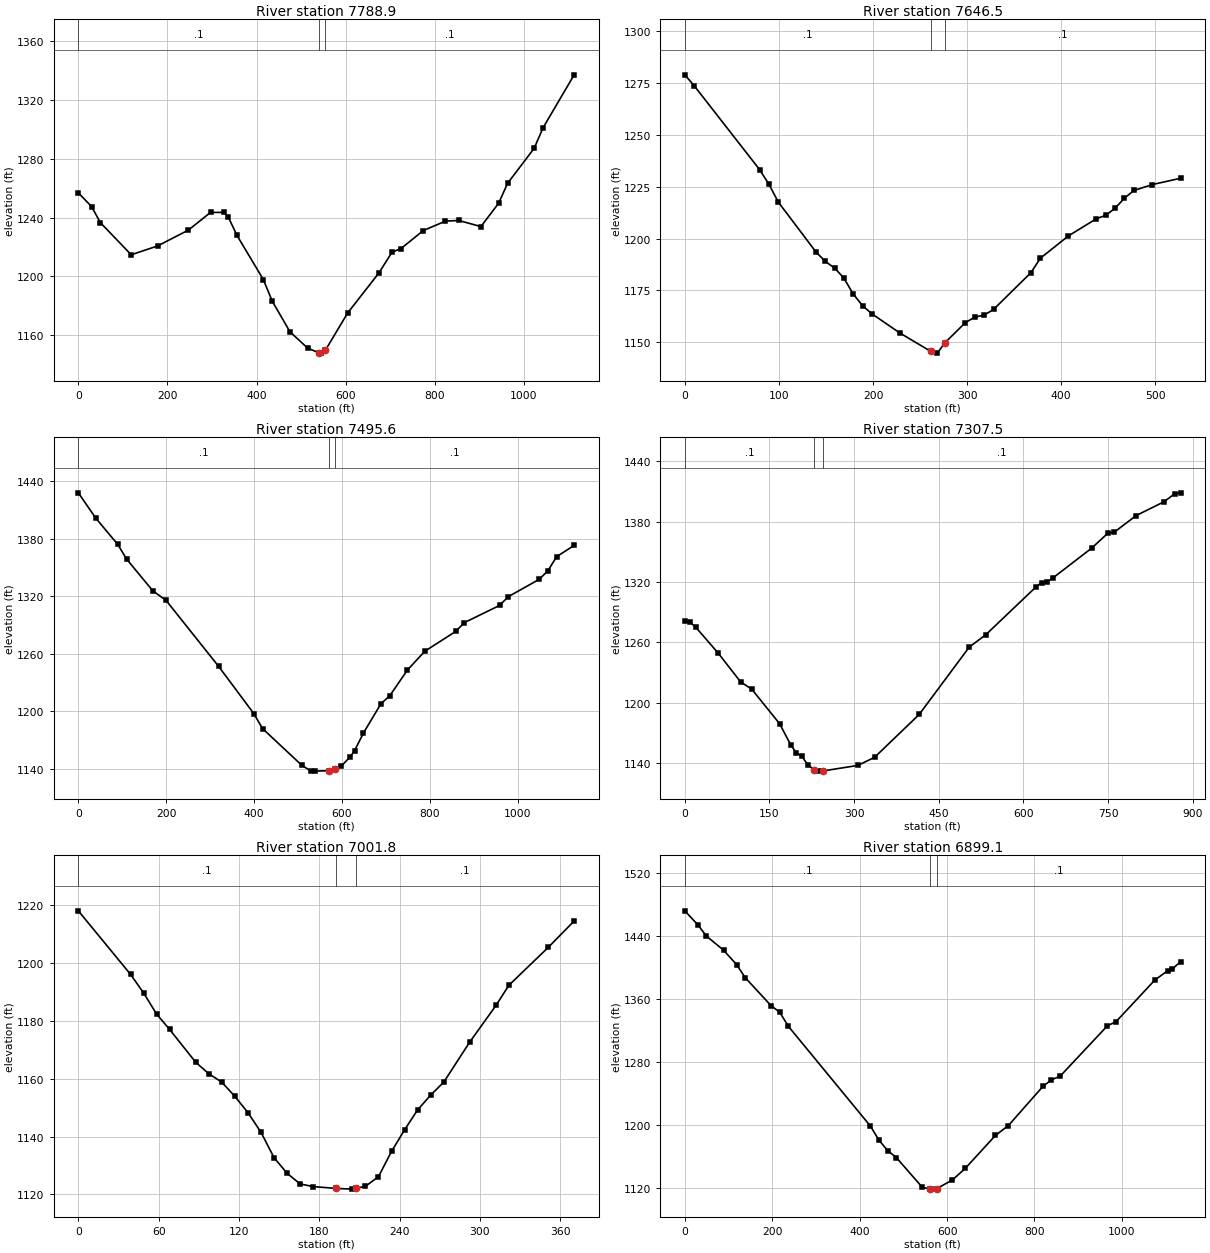
Type RM Length L Ch R = 1 ,7788.9  ,144.4,142.4,140.5
XS GIS Cut Line= 3
     1829465.694      355184.472     1829039.839      355273.661
     1828452.433      355611.665
#Sta/Elev= 30
       0 1256.78    29.7 1247.46    49.4 1236.55   118.7 1214.69     178  1220.7
   247.2 1231.49   296.7 1243.48   326.3 1243.49   336.2 1240.56     356 1227.87
   415.3 1197.81   435.1  1183.2     475 1162.32   514.8 1151.21   539.7 1148.08
   544.7 1147.83   554.7 1149.91   604.5 1175.14   674.3 1202.21   704.2 1216.47
   724.1 1218.89     774 1231.09   823.8 1237.54   853.7 1237.99   903.5 1233.85
   943.4 1249.77   963.3 1263.21  1023.1 1287.09    1043    1301  1112.8    1337
#Mann= 3 , 0 , 0
       0      .1       0   539.7    .045       0   554.7      .1       0
Bank Sta=539.7,554.7
XS Rating Curve= 0 ,0
Exp/Cntr=0.3,0.1

Type RM Length L Ch R = 1 ,7646.5  ,155.3,150.9,145.8
XS GIS Cut Line= 2
     1829114.185      355044.319     1828681.037      355344.289
#Sta/Elev= 30
       0 1278.99     9.9 1273.77    79.5 1233.27    89.5 1226.12    99.4 1217.59
   139.2 1193.65   149.1 1189.06   159.1 1185.82     169    1181   178.9  1173.3
   188.9 1167.67   198.8 1163.73   228.6 1154.46   261.2 1145.65   268.4 1144.76
   276.2 1149.67   298.2 1159.49   308.2 1162.13   318.1  1163.1   328.1 1165.83
   367.8 1183.57   377.8  1190.5   407.6 1201.28   437.4 1209.59   447.4 1211.24
   457.3 1214.67   467.2  1219.5   477.2  1223.2     497 1226.08   526.9 1229.11
#Mann= 3 , 0 , 0
       0      .1       0   261.2    .045       0   276.2      .1       0
Bank Sta=261.2,276.2
XS Rating Curve= 0 ,0
Exp/Cntr=0.3,0.1

Type RM Length L Ch R = 1 ,7495.6  ,202.6,188,170
XS GIS Cut Line= 3
     1829176.458      354723.579     1828760.855      355140.725
     1828405.153      355546.319
#Sta/Elev= 30
       0    1428    39.9 1401.44    89.8 1374.06   109.8 1358.79   169.7 1325.56
   199.6 1315.68   319.4 1246.64   399.2 1197.47   419.2 1181.78     509 1143.21
     529 1137.54   538.9 1137.33   569.9 1137.77   584.9 1139.51   598.8 1142.77
   618.8 1152.39   628.8 1158.84   648.8 1177.14   688.8 1207.83   708.7 1216.03
   748.7 1242.82   788.6  1262.6   858.6 1283.18   878.6 1292.48   958.5 1310.37
   978.5 1319.55  1048.4 1337.55  1068.4 1346.47  1088.4 1361.29  1128.3 1373.14
#Mann= 3 , 0 , 0
       0      .1       0   569.9    .045       0   584.9      .1       0
Bank Sta=569.9,584.9
XS Rating Curve= 0 ,0
Exp/Cntr=0.3,0.1

Type RM Length L Ch R = 1 ,7307.5  ,286.6,305.5,328.7
XS GIS Cut Line= 3
     1828719.827      354734.004     1828665.521      355096.038
     1828330.785      355484.264
#Sta/Elev= 30
       0 1281.18     9.9 1279.69    19.8 1274.75    59.4 1249.06    98.9 1220.61
   118.7 1213.33   168.2 1178.92     188 1157.61   197.9 1150.05   207.8 1146.53
   217.7 1138.25   229.2 1133.32   237.5 1131.89   244.2 1132.02   306.7 1137.56
   336.4 1145.65   415.4 1188.25   504.1  1255.2   533.7 1267.64   622.4 1315.05
   632.2 1319.35   642.1 1320.17     652  1323.8     721  1353.6   750.5 1368.85
   760.4  1369.2   799.8 1385.96   849.1 1399.67   868.8 1407.88   878.7  1408.6
#Mann= 3 , 0 , 0
       0      .1       0   229.2    .045       0   244.2      .1       0
Bank Sta=229.2,244.2
XS Rating Curve= 0 ,0
Exp/Cntr=0.3,0.1

Type RM Length L Ch R = 1 ,7001.8  ,106.6,102.7,98.3
XS GIS Cut Line= 2
     1828600.873      354775.379     1828291.851       354979.67
#Sta/Elev= 30
       0 1217.96      39 1196.01    48.7 1189.62    58.5 1182.29    68.2 1176.97
    87.7 1165.64    97.5 1161.67   107.2 1158.76     117 1153.82   126.7 1148.25
   136.5 1141.42   146.2 1132.68     156 1127.27   165.7 1123.61   175.5 1122.69
   192.6 1122.07   204.7 1121.82   207.6 1122.11   214.5  1122.8   224.2 1126.11
     234 1134.88   243.7 1142.28   253.5 1149.23   263.2 1154.29     273 1158.79
   292.5  1172.7     312 1185.28   321.7 1192.27     351 1205.31   370.4 1214.45
#Mann= 3 , 0 , 0
       0      .1       0   192.6    .045       0   207.6      .1       0
Bank Sta=192.6,207.6
XS Rating Curve= 0 ,0
Exp/Cntr=0.3,0.1

Type RM Length L Ch R = 1 ,6899.1  ,154.8,136.2,118.2
XS GIS Cut Line= 3
     1828794.542      354408.569      1828370.01      354807.596
     1827990.899       355208.39
#Sta/Elev= 30
       0 1472.05    29.6 1454.47    49.4 1440.05    88.9    1422   118.5 1403.78
   138.2 1387.25   197.5 1351.62   217.2 1343.32     237 1325.44   424.6  1198.9
   444.4 1180.86   464.1 1167.73   483.9 1158.93   543.1 1121.29   561.9 1118.88
   562.9 1118.86   576.9 1119.65   612.2 1130.48   641.7 1145.22   710.7 1187.04
   740.2 1199.47   819.1 1249.11   838.8 1257.59   858.5 1262.12   966.8 1326.11
   986.5 1331.38  1075.2 1384.13  1104.8 1396.13  1114.6 1397.84  1134.3 1407.62
#Mann= 3 , 0 , 0
       0      .1       0   561.9    .045       0   576.9      .1       0
Bank Sta=561.9,576.9
XS Rating Curve= 0 ,0
Exp/Cntr=0.3,0.1

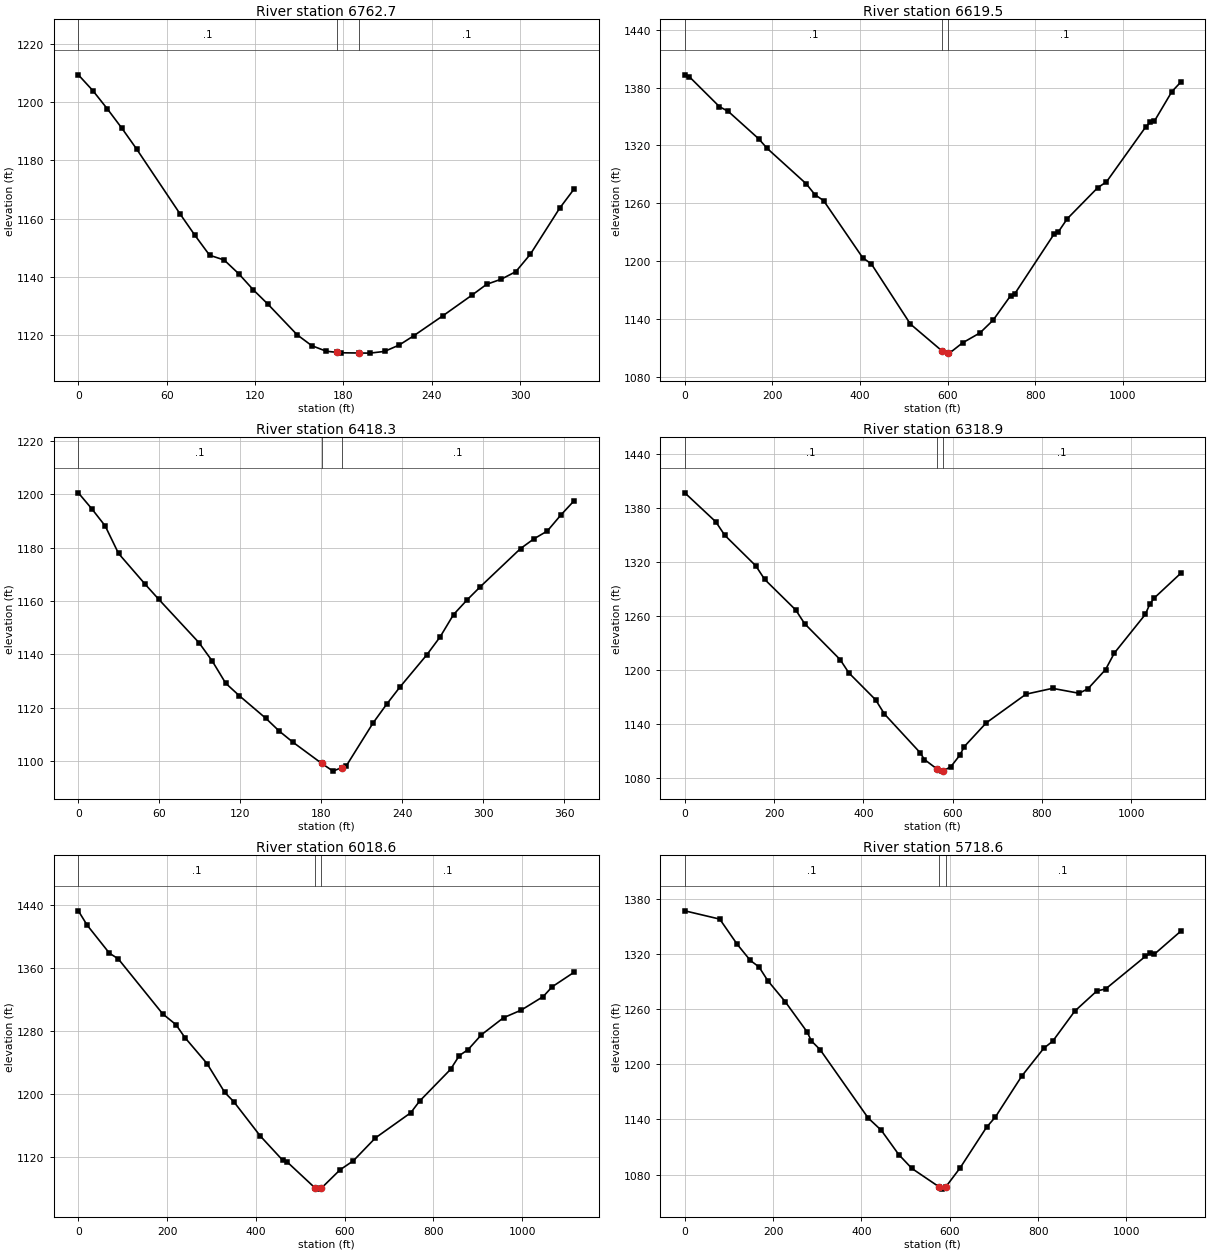
Type RM Length L Ch R = 1 ,6762.7  ,130.6,143.3,153.6
XS GIS Cut Line= 2
     1828297.354      354534.458     1828284.075      354870.835
#Sta/Elev= 30
       0 1209.37     9.9 1203.93    19.8 1197.62    29.7 1190.96    39.6 1183.89
    69.3 1161.48    79.2 1154.29    89.1  1147.5      99 1145.85   108.9 1141.13
   118.8 1135.61   128.7 1130.71   148.5 1120.22   158.4 1116.49   168.3 1114.56
   175.8 1114.16   178.2 1114.03   190.8 1113.95     198 1113.91   207.9  1114.5
   217.8 1116.68   227.7 1119.86   247.5 1126.73   267.3 1133.83   277.2 1137.52
   287.1 1139.27     297 1141.86   306.9 1147.86   326.7 1163.58   336.6 1170.24
#Mann= 3 , 0 , 0
       0      .1       0   175.8    .045       0   190.8      .1       0
Bank Sta=175.8,190.8
XS Rating Curve= 0 ,0
Exp/Cntr=0.3,0.1

Type RM Length L Ch R = 1 ,6619.5  ,188.8,201.2,216
XS GIS Cut Line= 3
     1828495.718      354189.394      1828154.84      354676.134
     1827900.087      355149.594
#Sta/Elev= 30
       0 1393.19     9.9 1391.41    79.2 1360.15      99 1355.39   168.4    1327
   188.2 1316.88   277.3  1280.2   297.1 1268.97   316.9 1262.79   406.1 1203.64
   425.9  1197.2     515 1134.88   586.7 1107.21   601.7 1104.76   604.2 1104.74
   634.1 1115.39   673.9 1125.73   703.8 1138.88   743.6 1164.16   753.5  1166.4
   843.1 1228.22   853.1 1230.63     873 1243.98   942.7 1276.25   962.6 1282.23
  1052.2 1339.19  1062.2 1343.86  1072.1 1345.26    1112 1375.85  1131.9 1385.45
#Mann= 3 , 0 , 0
       0      .1       0   586.7    .045       0   601.7      .1       0
Bank Sta=586.7,601.7
XS Rating Curve= 0 ,0
Exp/Cntr=0.3,0.1

Type RM Length L Ch R = 1 ,6418.3  ,103,99.4,99.2
XS GIS Cut Line= 2
     1828180.064      354468.068       1827845.9      354620.766
#Sta/Elev= 30
       0 1200.59     9.9 1194.64    19.9 1188.16    29.8 1177.82    49.6 1166.23
    59.6 1160.61    89.4 1144.34    99.3 1137.39   109.2 1129.11   119.2 1124.46
     139 1115.92     149 1111.09   158.9 1107.02   180.2 1099.07   188.7 1096.12
   195.2 1097.44   198.6 1098.13   218.4  1114.2   228.4  1121.2   238.3 1127.68
   258.2 1139.77   268.1 1146.52     278 1154.88     288 1160.36   297.9 1165.36
   327.7 1179.68   337.6 1183.32   347.5 1186.25   357.5 1192.23   367.4 1197.64
#Mann= 3 , 0 , 0
       0      .1       0   180.2    .045       0   195.2      .1       0
Bank Sta=180.2,195.2
XS Rating Curve= 0 ,0
Exp/Cntr=0.3,0.1

Type RM Length L Ch R = 1 ,6318.9  ,305.5,300.3,293.2
XS GIS Cut Line= 3
     1828440.002      354127.462     1827976.135      354452.987
     1827481.672      354680.214
#Sta/Elev= 30
       0 1396.82    69.6 1364.52    89.5 1349.67   159.1 1315.63     179 1300.53
   248.6 1266.55   268.4 1251.36     348 1211.38   367.8 1196.46   427.5 1166.66
   447.4  1150.8   526.9 1108.05   536.9 1100.25   564.4 1089.96   576.6 1087.34
   579.4 1087.61   596.4 1092.45   616.2 1105.06   626.1 1114.59   675.5 1141.07
   764.6 1172.94   823.9  1179.4   883.3 1173.93   903.1 1178.83   942.7 1200.26
   962.4 1218.64  1031.7 1261.55  1041.6 1272.79  1051.5 1279.73  1110.9 1307.22
#Mann= 3 , 0 , 0
       0      .1       0   564.4    .045       0   579.4      .1       0
Bank Sta=564.4,579.4
XS Rating Curve= 0 ,0
Exp/Cntr=0.3,0.1

Type RM Length L Ch R = 1 ,6018.6  ,297.8,300,297.2
XS GIS Cut Line= 3
     1828216.285      353792.666     1827847.018      354186.929
     1827421.624      354577.272
#Sta/Elev= 30
       0 1432.78      20 1414.45      70 1378.91      90 1371.65   190.1  1301.7
   220.1  1287.9   240.1  1271.6   290.1 1238.41   330.1 1201.62   350.1 1190.08
   410.1 1146.26   460.2 1115.66   470.2 1113.47   532.7 1080.59   540.2 1078.67
   547.7 1079.88     590 1103.33   619.8  1114.7   669.6 1143.84   749.2 1175.84
   769.1 1190.64   838.8 1230.99   858.7 1248.62   878.6 1256.27   908.5 1275.09
   958.3 1296.77   998.1 1306.42  1047.8 1323.71  1067.8 1336.07  1117.5 1354.69
#Mann= 3 , 0 , 0
       0      .1       0   532.7    .045       0   547.7      .1       0
Bank Sta=532.7,547.7
XS Rating Curve= 0 ,0
Exp/Cntr=0.3,0.1

Type RM Length L Ch R = 1 ,5718.6  ,189.5,201.2,216.1
XS GIS Cut Line= 3
     1828030.783      353644.446     1827593.375      354030.307
     1827243.039      354440.477
#Sta/Elev= 30
       0 1366.89    79.1 1357.89   118.6 1330.54   148.3 1312.97   168.1 1305.82
   187.8    1291   227.4 1268.05   276.8  1235.3   286.7 1225.38   306.5 1215.84
   415.2 1141.57   444.9 1128.23   484.4 1101.84   514.1 1086.75   575.8 1066.68
   583.3 1064.22   590.8 1066.58   623.2 1087.16   683.2 1131.47   703.2 1142.61
   763.1 1187.24     813 1217.51     833 1225.06     883  1257.8   932.9  1279.7
   952.9 1281.94  1042.8 1317.31  1052.8 1320.52  1062.8 1319.56  1122.7  1344.6
#Mann= 3 , 0 , 0
       0      .1       0   575.8    .045       0   590.8      .1       0
Bank Sta=575.8,590.8
XS Rating Curve= 0 ,0
Exp/Cntr=0.3,0.1

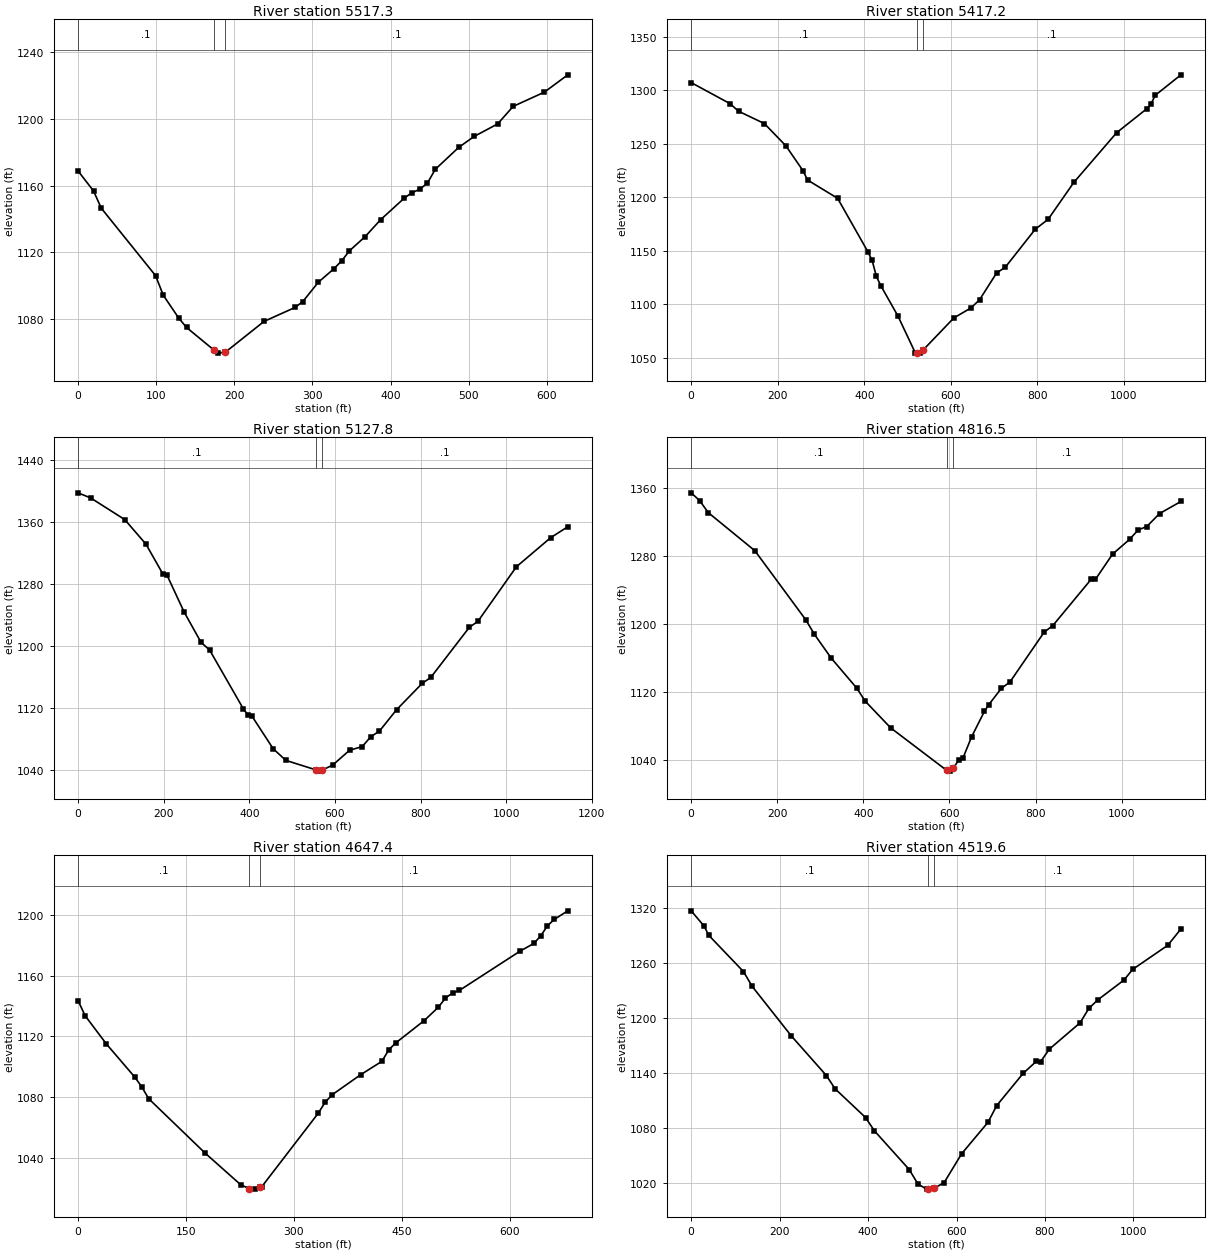
Type RM Length L Ch R = 1 ,5517.3  ,103.8,100.1,92.3
XS GIS Cut Line= 3
     1827690.989      353816.337      1827390.02      353879.408
     1827160.974      354101.815
#Sta/Elev= 30
       0 1168.79    19.8 1156.78    29.8 1146.38    99.2 1105.93   109.1 1094.15
     129 1080.36   138.9 1074.79   173.5 1061.42   178.6  1059.4   188.5 1059.94
   238.1 1078.45   277.8 1086.83   287.7 1090.36   307.5 1101.93   327.5 1110.06
   337.4 1114.77   347.4 1120.84   367.4 1129.32   387.3 1139.51   417.2  1152.3
   427.2  1155.7   437.2  1157.7   447.2 1161.51   457.2 1169.72   487.1 1182.86
     507 1189.49     537 1196.98   556.9 1207.52   596.8 1216.05   626.8 1226.46
#Mann= 3 , 0 , 0
       0      .1       0   173.5    .045       0   188.5      .1       0
Bank Sta=173.5,188.5
XS Rating Curve= 0 ,0
Exp/Cntr=0.3,0.1

Type RM Length L Ch R = 1 ,5417.2  ,310.7,289.4,272.3
XS GIS Cut Line= 3
     1827981.851        353564.6      1827481.05      353759.841
      1827016.12      354129.684
#Sta/Elev= 30
       0 1307.11    89.6 1287.46   109.5 1280.34   169.2  1268.8     219 1247.95
   258.8 1224.53   268.8  1216.1   338.4 1198.97   408.1 1149.23   418.1 1140.92
     428 1126.05     438 1117.46   477.8 1088.96   517.6  1054.8   520.8 1054.66
   527.6 1054.35   535.8 1057.22   606.8 1087.18   646.4 1096.57   666.2 1104.11
   705.8 1129.32   725.6 1134.49     795 1170.11   824.7 1179.32   884.1 1213.84
   983.1  1260.3  1052.4 1282.56  1062.3 1287.02  1072.2 1295.22  1131.6 1314.36
#Mann= 3 , 0 , 0
       0      .1       0   520.8    .045       0   535.8      .1       0
Bank Sta=520.8,535.8
XS Rating Curve= 0 ,0
Exp/Cntr=0.3,0.1

Type RM Length L Ch R = 1 ,5127.8  ,302.7,311.3,316.5
XS GIS Cut Line= 3
     1827421.456      353054.391     1827248.404      353695.145
     1826954.883      354074.824
#Sta/Elev= 30
       0 1398.17    29.7 1391.52     109 1363.66   158.5 1332.02   198.1 1293.48
     208 1291.64   247.6  1244.5   287.3 1205.16   307.1 1195.46   386.3 1119.15
   396.2 1111.91   406.2 1109.95   455.7 1067.88   485.4 1052.88   554.7 1040.81
   564.6 1039.04   569.7 1040.38   594.4 1046.74     634 1065.92   663.7 1070.75
   683.7 1083.52   703.7 1090.62   743.7 1118.23   803.7 1152.28   823.7 1159.94
   913.7  1224.6   933.7 1232.28  1023.6 1302.74  1103.6 1340.28  1143.6 1354.38
#Mann= 3 , 0 , 0
       0      .1       0   554.7    .045       0   569.7      .1       0
Bank Sta=554.7,569.7
XS Rating Curve= 0 ,0
Exp/Cntr=0.3,0.1

Type RM Length L Ch R = 1 ,4816.5  ,159,169.1,182.7
XS GIS Cut Line= 3
     1827343.633       353016.49     1826981.767      353497.251
     1826729.076      353970.001
#Sta/Elev= 30
       0 1354.09    19.7 1344.94    39.5  1330.9     148 1285.94   266.3 1204.63
   286.1 1187.72   325.5 1159.46   384.7 1124.24   404.4 1108.87   463.6 1077.43
   593.4 1027.52   601.7 1026.57   608.4 1029.68   621.6 1039.52   631.5    1042
   651.4 1066.84   681.1 1096.76   691.1 1104.63   720.8 1124.05   740.7 1131.54
   820.1 1190.17     840 1197.74   929.3 1252.35   939.2 1252.28     979 1281.96
  1018.6 1299.34  1038.5 1310.43  1058.4 1314.39  1088.1 1329.67  1137.8 1343.91
#Mann= 3 , 0 , 0
       0      .1       0   593.4    .045       0   608.4      .1       0
Bank Sta=593.4,608.4
XS Rating Curve= 0 ,0
Exp/Cntr=0.3,0.1

Type RM Length L Ch R = 1 ,4647.4  ,131,127.7,122.9
XS GIS Cut Line= 3
     1827107.848      353244.308     1826645.077      353482.986
     1826544.302       353607.63
#Sta/Elev= 30
       0  1143.6     9.8  1133.6    39.3    1115    78.6 1093.22    88.4 1086.81
    98.2 1078.83   176.8 1042.88     226 1022.11   238.1 1019.44   245.6 1019.14
   253.1 1020.33   255.4 1020.69     334 1069.21   343.9 1076.68   353.7 1081.52
     393 1094.64   422.4 1103.42   432.3 1111.17   442.1 1115.74   481.4 1130.37
     501 1139.16   510.9 1145.18   520.7  1148.6   530.1  1150.2     615 1176.27
   633.8 1181.24   643.3 1186.22   652.7 1192.89   662.1 1197.08     681 1202.77
#Mann= 3 , 0 , 0
       0      .1       0   238.1    .045       0   253.1      .1       0
Bank Sta=238.1,253.1
XS Rating Curve= 0 ,0
Exp/Cntr=0.3,0.1

Type RM Length L Ch R = 1 ,4519.6  ,313.2,305.1,298.7
XS GIS Cut Line= 3
      1827274.49      352927.078     1826833.661      353242.971
     1826397.971      353602.937
#Sta/Elev= 30
       0 1317.32    29.6 1300.45    39.4 1290.79   118.3 1250.98     138 1234.79
   226.8 1180.58   305.7 1137.54   325.4 1123.06   394.4 1091.67   414.1  1077.3
     493 1034.93   512.8 1019.08   532.5 1013.52   534.8  1013.6   549.8 1014.53
   572.1 1020.69   611.7 1052.18   671.2 1086.46     691 1104.79   750.5 1139.77
   780.3 1152.96   790.2 1152.63     810 1166.38   879.4 1195.04   899.3 1210.79
   919.1 1219.96   978.6 1241.71   998.4 1253.43  1077.7 1279.66  1107.5 1297.53
#Mann= 3 , 0 , 0
       0      .1       0   534.8    .045       0   549.8      .1       0
Bank Sta=534.8,549.8
XS Rating Curve= 0 ,0
Exp/Cntr=0.3,0.1

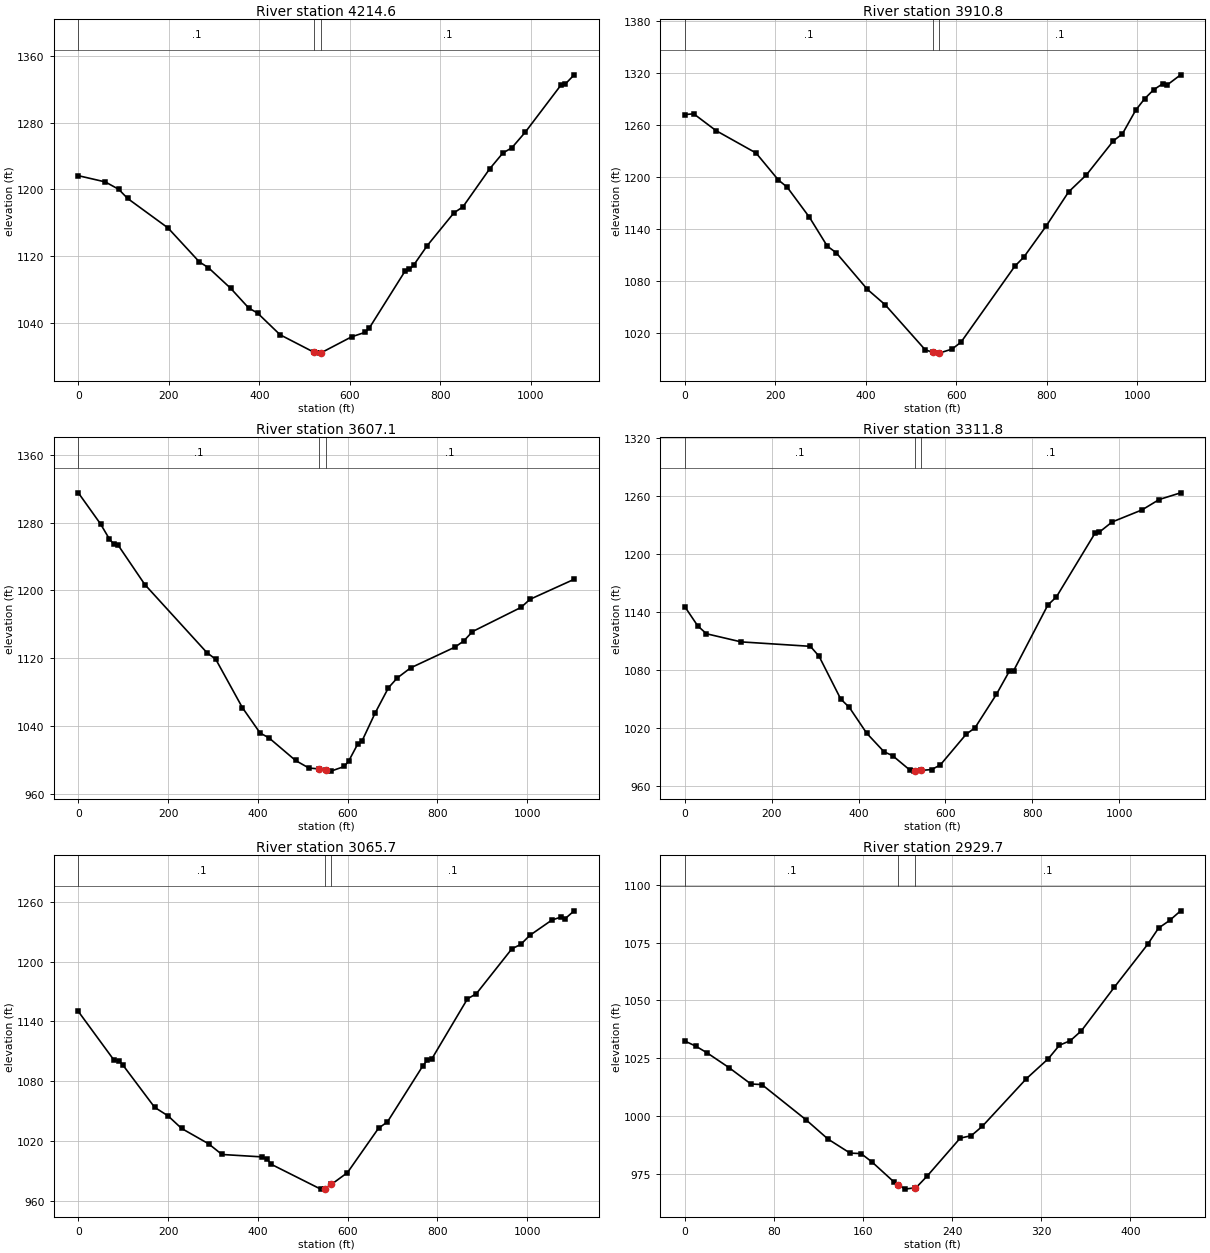
Type RM Length L Ch R = 1 ,4214.6  ,305.6,303.8,301.4
XS GIS Cut Line= 3
     1826900.258      352605.763       1826597.9      353059.323
     1826278.934      353508.718
#Sta/Elev= 30
       0 1216.46    59.5 1209.01    89.2  1200.2     109 1189.21   198.2    1154
   267.6  1113.3   287.4 1106.51     337 1081.65   376.6 1058.26   396.4 1052.08
     446 1026.23     522    1005   535.2 1004.24     537 1004.72   604.2 1023.74
   633.7 1029.06   643.5 1034.43   722.2 1102.22   732.1 1104.43   741.9 1109.86
   771.4 1132.84   830.5 1172.08   850.2 1179.13   909.2 1224.48   938.7 1243.62
   958.4 1249.79   987.9 1268.34  1066.7 1324.59  1076.5 1326.02  1096.2 1337.08
#Mann= 3 , 0 , 0
       0      .1       0     522    .045       0     537      .1       0
Bank Sta=522,537
XS Rating Curve= 0 ,0
Exp/Cntr=0.3,0.1

Type RM Length L Ch R = 1 ,3910.8  ,302.7,303.6,305.2
XS GIS Cut Line= 3
     1826598.088       352448.17     1826329.554      352929.594
     1826072.673      353410.184
#Sta/Elev= 30
       0 1271.95    19.7 1272.82    68.9 1253.47   157.5 1227.59   206.7 1196.56
   226.4 1188.11   275.6 1153.36     315 1120.09   334.7  1112.5   403.6 1070.23
     443 1052.42   531.6 1000.38   548.1  997.63   561.2   996.6   563.1  996.73
   590.9 1001.28   610.7 1009.27   729.6 1096.91   749.4 1107.33     799 1143.32
   848.5 1182.67   888.1 1202.45   947.6 1241.69   967.4 1249.56   997.1 1277.17
  1016.9 1290.36  1036.7 1300.66  1056.6 1307.49  1066.5 1306.14  1096.2 1317.82
#Mann= 3 , 0 , 0
       0      .1       0   548.1    .045       0   563.1      .1       0
Bank Sta=548.1,563.1
XS Rating Curve= 0 ,0
Exp/Cntr=0.3,0.1

Type RM Length L Ch R = 1 ,3607.1  ,307.4,295.2,282.8
XS GIS Cut Line= 3
     1826387.286       352278.35     1826100.416      352739.675
     1825796.655      353211.897
#Sta/Elev= 30
       0 1315.07    49.4 1278.41    69.1  1260.7      79 1254.43    88.9 1253.15
   148.2 1206.85   286.4 1126.59   306.2 1118.72   365.5 1061.68     405 1031.73
   424.7 1026.03     484  999.32   513.6  990.46   535.7  989.43   550.7  988.14
     563  986.78   592.5  992.28   602.4  998.71     622 1018.26   631.9 1022.16
   661.4 1055.46     691 1085.19   710.7 1096.74   740.3 1108.57   838.8 1132.98
   858.5 1140.19   878.2  1151.4   986.5 1179.97  1006.2 1189.43  1104.7 1213.09
#Mann= 3 , 0 , 0
       0      .1       0   535.7    .045       0   550.7      .1       0
Bank Sta=535.7,550.7
XS Rating Curve= 0 ,0
Exp/Cntr=0.3,0.1

Type RM Length L Ch R = 1 ,3311.8  ,239.1,246.1,253.4
XS GIS Cut Line= 3
     1825864.713       352050.15     1825848.156      352737.778
     1825720.133      353172.936
#Sta/Elev= 30
       0 1145.65    29.9 1125.64    49.8 1117.56   129.6 1109.13   289.1 1104.52
     309 1094.28   358.9 1049.93   378.8 1041.18   418.7 1014.48   458.6  995.23
   478.5  991.15   518.4  976.16   528.3  975.16   528.8  975.18   543.8   975.9
   568.2   976.8   588.1  981.53     648 1013.58   667.9 1019.97   717.4 1054.79
     747 1078.66   756.8 1079.12   835.7  1147.3   855.5 1155.79   944.2 1221.72
   954.1 1222.85   983.6  1233.4  1052.7 1245.98  1092.1 1256.71  1141.4 1263.64
#Mann= 3 , 0 , 0
       0      .1       0   528.8    .045       0   543.8      .1       0
Bank Sta=528.8,543.8
XS Rating Curve= 0 ,0
Exp/Cntr=0.3,0.1

Type RM Length L Ch R = 1 ,3065.7  ,141.6,136,130.1
XS GIS Cut Line= 3
     1825800.444      352046.364     1825633.285      352570.349
     1825455.928      353095.779
#Sta/Elev= 30
       0 1149.93      80  1100.7      90 1100.55     100 1095.67     170 1053.65
     200 1045.04     230 1032.47     290  1017.1     320 1006.32     410 1003.87
     420 1001.88     430  996.42     540  971.53     549  972.12     564  976.36
   599.5  988.08   668.8 1032.68   688.6 1039.02   767.9 1095.57   777.8 1101.29
   787.7 1102.46   866.9 1162.57   886.7 1167.76   965.9 1212.86   985.7 1217.26
  1005.5 1226.22    1055 1241.71  1074.8 1244.62  1084.8 1243.19  1104.6 1250.96
#Mann= 3 , 0 , 0
       0      .1       0     549    .045       0     564      .1       0
Bank Sta=549,564
XS Rating Curve= 0 ,0
Exp/Cntr=0.3,0.1

Type RM Length L Ch R = 1 ,2929.7  ,204.7,218.6,232.2
XS GIS Cut Line= 2
     1825514.006      352345.285     1825484.834      352789.492
#Sta/Elev= 30
       0 1032.47     9.9 1030.24    19.8 1027.43    39.6 1021.01    59.4  1013.9
    69.2 1013.67   108.8  998.47   128.6  990.11   148.4  984.07   158.3  983.85
   168.2  980.19     188  971.52   191.8  970.35   197.8  968.51   206.8  969.11
   207.7  969.17   217.6  974.14   247.3  990.54   257.2  991.58   267.1  995.62
   306.7  1016.2   326.4 1024.84   336.4 1030.66   346.2 1032.62   356.1 1036.89
   385.8 1055.79   415.5 1074.15   425.4 1081.24   435.3 1084.53   445.2 1088.69
#Mann= 3 , 0 , 0
       0      .1       0   191.8    .045       0   206.8      .1       0
Bank Sta=191.8,206.8
XS Rating Curve= 0 ,0
Exp/Cntr=0.3,0.1

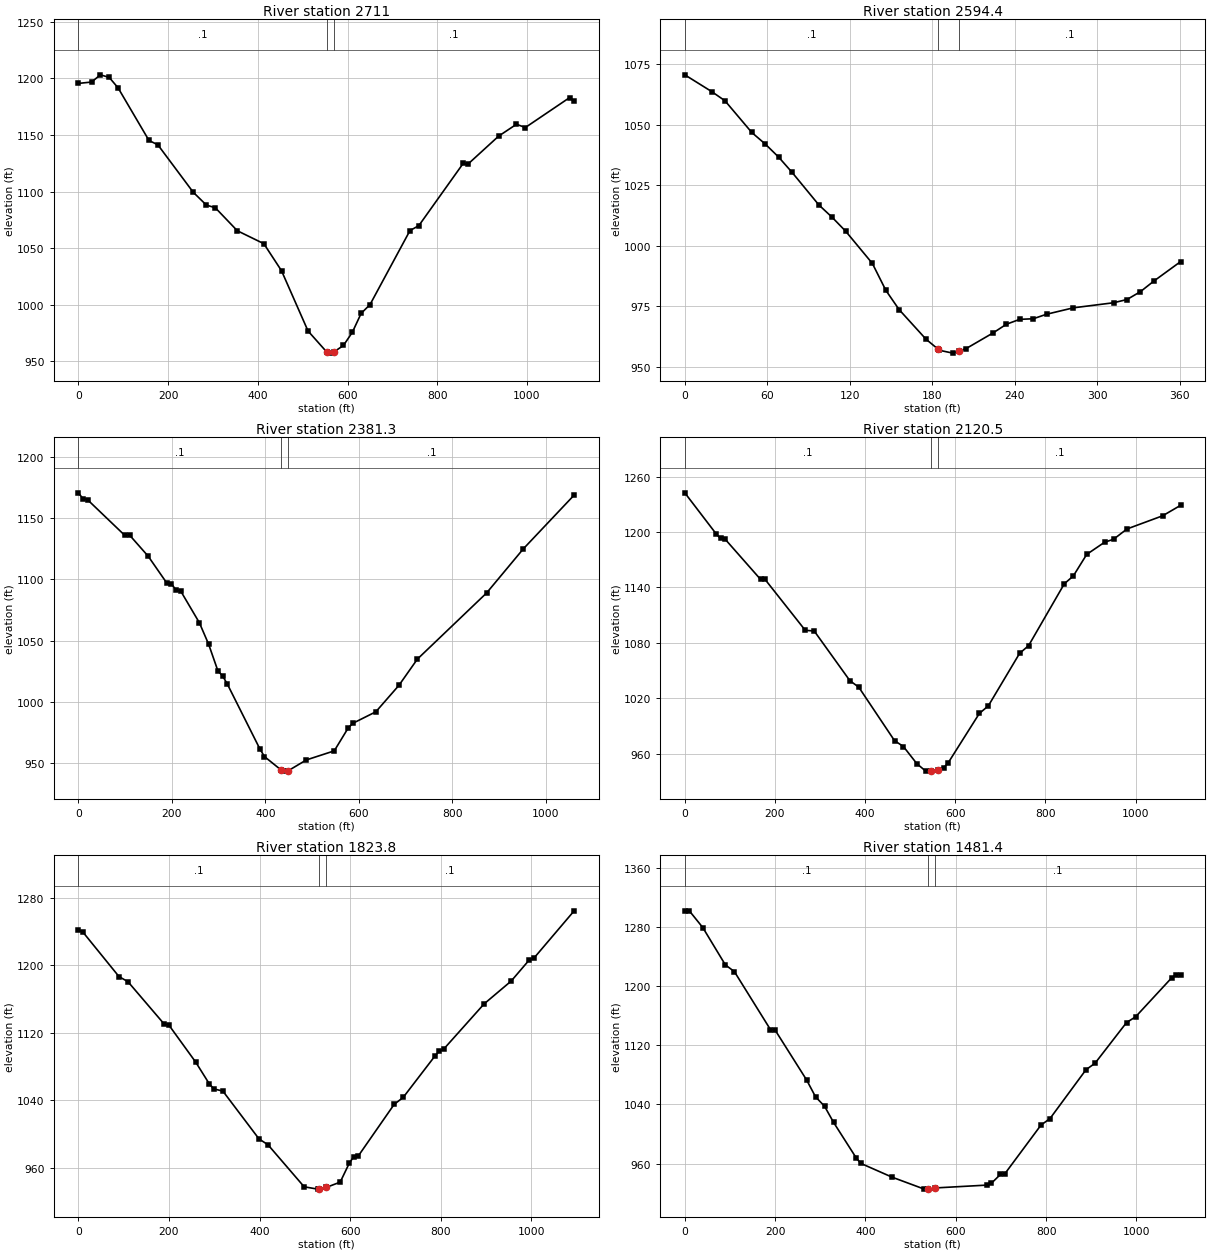
Type RM Length L Ch R = 1 ,2711    ,112.4,116.9,121.8
XS GIS Cut Line= 3
     1825672.428      351990.977     1825321.142      352428.653
     1824992.176      352861.884
#Sta/Elev= 30
       0 1195.48    29.5 1196.69    49.2 1203.06    68.9 1200.77    88.6 1191.54
   157.5  1145.1   177.2  1141.3     256 1099.45   285.5 1088.04   305.2 1085.75
   354.4 1065.41   413.5 1053.99   452.9 1030.11     512  976.92   554.4  958.05
   561.2  957.38   569.4  958.39   590.9  964.12   610.7  975.74   630.4  992.47
   650.2 1000.24   739.2 1065.56     759 1069.93   857.9  1124.9   867.8 1123.98
     937 1148.99   976.6 1159.41   996.4 1156.54  1095.3 1183.02  1105.2 1179.63
#Mann= 3 , 0 , 0
       0      .1       0   554.4    .045       0   569.4      .1       0
Bank Sta=554.4,569.4
XS Rating Curve= 0 ,0
Exp/Cntr=0.3,0.1

Type RM Length L Ch R = 1 ,2594.4  ,236.9,212.8,188.7
XS GIS Cut Line= 2
     1825385.384      352231.249     1825108.252      352461.972
#Sta/Elev= 30
       0 1070.71    19.5 1063.81    29.2    1060    48.7  1046.9    58.5 1042.12
    68.2 1036.74      78 1030.42    97.5 1016.95   107.2 1011.82     117 1006.09
   136.4  992.79   146.2  981.68   155.9  973.68   175.4  961.49   184.2  957.36
   185.2  956.89   194.9  955.72   199.2  956.56   204.7  957.63   224.2  964.07
   233.9  967.66   243.6  969.68   253.4  969.92   263.1  971.79   282.6  974.44
   311.9  976.54   321.6  977.87   331.4  981.13   341.1  985.48   360.6  993.54
#Mann= 3 , 0 , 0
       0      .1       0   184.2    .045       0   199.2      .1       0
Bank Sta=184.2,199.2
XS Rating Curve= 0 ,0
Exp/Cntr=0.3,0.1

Type RM Length L Ch R = 1 ,2381.3  ,257.7,260.8,263.6
XS GIS Cut Line= 3
     1825028.692      351794.998     1825108.252      352346.611
      1824929.31      352816.934
#Sta/Elev= 30
       0 1170.77      10 1165.98    19.9 1165.06    99.5 1135.96   109.5 1136.28
   149.3 1119.07   189.1 1097.16     199 1096.55     209 1091.37     219 1090.54
   258.8 1064.76   278.7 1047.14   298.6 1025.31   308.5  1021.3   318.5 1014.76
   388.1   961.8   398.1   955.4   434.3  944.28   437.9  943.53   449.3  943.94
   487.7  952.67   547.4  960.08     577  978.65   586.9  982.54   636.3  991.97
   685.6 1013.52   725.1 1034.96   873.1 1088.96     952 1125.12  1060.5 1168.93
#Mann= 3 , 0 , 0
       0      .1       0   434.3    .045       0   449.3      .1       0
Bank Sta=434.3,449.3
XS Rating Curve= 0 ,0
Exp/Cntr=0.3,0.1

Type RM Length L Ch R = 1 ,2120.5  ,288.1,296.6,304.2
XS GIS Cut Line= 3
     1824834.787      351715.218     1824835.967      352269.361
     1824845.038      352814.872
#Sta/Elev= 30
       0 1242.52    69.3 1198.22    79.2 1193.05    89.1 1192.49   168.2 1148.66
   178.1 1148.66   267.2 1093.58     287 1092.87   366.1 1039.07   385.9 1031.95
   465.1  974.12   484.9   967.7   514.6  949.16   534.4  941.06   546.6  941.45
   561.6  942.73     574  944.72   583.9  949.85   653.3 1003.56   673.2 1011.77
   742.6 1068.66   762.5 1076.98   841.8 1144.06   861.7 1152.45   891.4 1175.82
   931.1 1189.01   950.9  1192.2   980.7 1203.36    1060 1217.69  1099.7 1228.99
#Mann= 3 , 0 , 0
       0      .1       0   546.6    .045       0   561.6      .1       0
Bank Sta=546.6,561.6
XS Rating Curve= 0 ,0
Exp/Cntr=0.3,0.1

Type RM Length L Ch R = 1 ,1823.8  ,343.3,342.4,342.7
XS GIS Cut Line= 3
     1824744.315      351696.973     1824545.255      352207.817
     1824389.827      352731.332
#Sta/Elev= 30
       0 1241.78      10 1239.31    89.7  1186.6   109.6 1180.47   189.4  1130.4
   199.4 1129.49   259.2 1085.17   289.1 1059.55     299 1053.58     319 1051.03
   398.7  994.44   418.7  987.39   498.4   937.7   528.3  934.93   532.1  935.31
   547.1  936.92     578  943.24   597.9  965.44   607.8   973.4   617.8  974.08
   697.2 1035.34     717 1043.48   786.6 1092.16   796.5  1098.3   806.4 1100.67
   895.8 1154.32   955.4 1181.28   995.1 1206.12    1005 1208.04  1094.4 1264.42
#Mann= 3 , 0 , 0
       0      .1       0   532.1    .045       0   547.1      .1       0
Bank Sta=532.1,547.1
XS Rating Curve= 0 ,0
Exp/Cntr=0.3,0.1

Type RM Length L Ch R = 1 ,1481.4  ,330.2,332.8,335.3
XS GIS Cut Line= 3
     1824400.977      351583.689     1824148.233      352330.699
      1824093.24       352634.94
#Sta/Elev= 30
       0 1301.52      10 1301.53    39.9 1278.88    89.8 1228.53   109.8 1219.41
   189.7 1141.05   199.6 1140.81   269.5 1073.26   289.5 1050.28   309.4 1037.57
   329.4 1015.74   379.3     968   389.3   960.5   459.2  941.69   529.1  925.87
   538.8   925.6   553.8  927.18   668.8  931.03   678.8  933.53   698.8  945.38
   708.8  946.51   788.6 1012.09   808.6 1020.93   888.3 1086.92   908.3 1095.65
   978.1 1150.66     998  1158.3  1077.8 1210.93  1087.8  1215.4  1097.8 1215.42
#Mann= 3 , 0 , 0
       0      .1       0   538.8    .045       0   553.8      .1       0
Bank Sta=538.8,553.8
XS Rating Curve= 0 ,0
Exp/Cntr=0.3,0.1

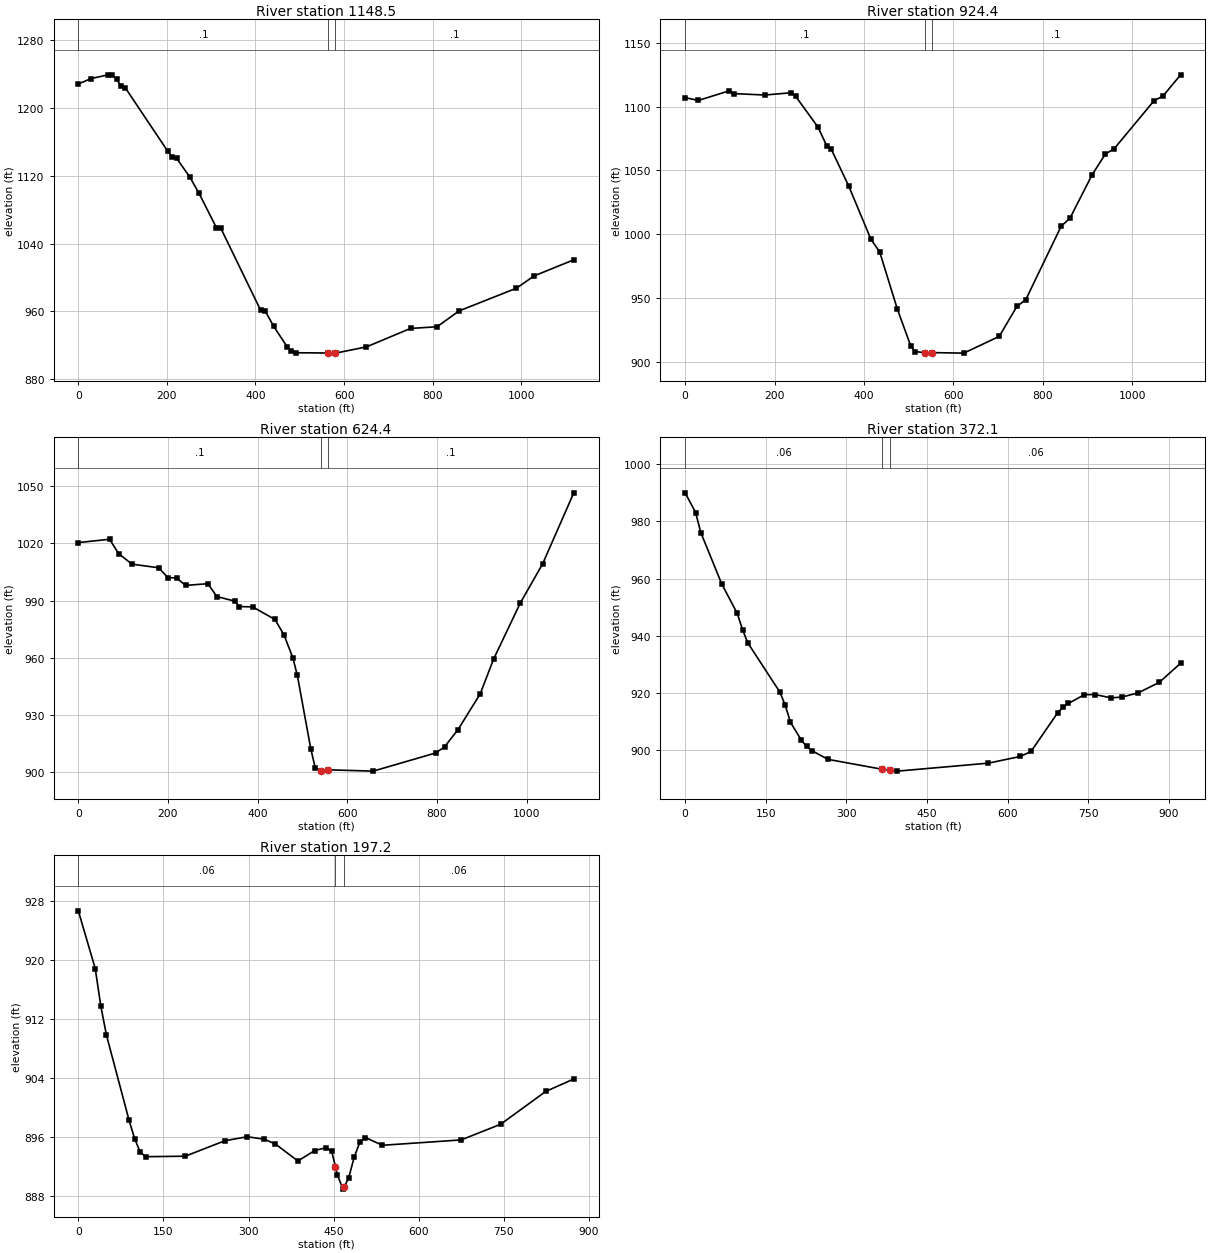
Type RM Length L Ch R = 1 ,1148.5  ,222.7,224.1,224.7
XS GIS Cut Line= 3
     1824176.079      351480.738      1824076.63      351645.161
     1823688.618      352486.457
#Sta/Elev= 30
       0 1228.31    28.8 1234.77    67.3 1239.17    76.9 1238.63    86.5 1234.15
    96.1 1226.09   105.7 1224.16   202.1 1148.87   212.1 1141.75     222 1140.59
   251.9 1118.37   271.8 1100.05   311.7 1058.84   321.7 1058.12   411.3  961.65
   421.3  960.94   441.2  942.25   471.1  918.49   481.1  913.21     491  911.18
   564.4  910.86   579.4  910.74   580.7  910.73   650.4  918.08     750  939.89
   809.8  941.82   859.6  960.55   989.1  987.36    1029 1001.85  1118.6 1020.86
#Mann= 3 , 0 , 0
       0      .1       0   564.4    .045       0   579.4      .1       0
Bank Sta=564.4,579.4
XS Rating Curve= 0 ,0
Exp/Cntr=0.3,0.1

Type RM Length L Ch R = 1 ,924.4   ,294.3,300,308.9
XS GIS Cut Line= 3
     1824002.853      351376.104     1823743.186      351854.196
     1823492.219      352359.713
#Sta/Elev= 30
       0 1106.98    29.7 1104.81    98.9 1112.41   108.8 1110.17   178.1 1109.05
   237.4 1110.85   247.3 1107.96   296.8  1084.1   316.5  1069.5   326.4 1066.95
     366 1037.74   415.5  996.22   435.2  986.22   474.8  941.38   504.5  912.82
   514.4  908.32   536.6  907.38   551.6  907.49   623.3  907.07   702.5  920.14
   742.1   943.6   761.9  948.87   841.1 1006.36   860.9 1012.69   910.4  1046.7
   940.1 1062.89   959.9  1067.1    1049 1104.65  1068.8 1108.24  1108.4 1124.86
#Mann= 3 , 0 , 0
       0      .1       0   536.6    .045       0   551.6      .1       0
Bank Sta=536.6,551.6
XS Rating Curve= 0 ,0
Exp/Cntr=0.3,0.1

Type RM Length L Ch R = 1 ,624.4   ,237.1,252.2,264.8
XS GIS Cut Line= 3
     1823893.665      351286.101     1823525.276       351692.21
     1823111.384      352064.433
#Sta/Elev= 30
       0 1020.33    69.8 1022.06    89.7 1014.61   119.6 1009.02   179.4 1007.14
   199.4 1002.04   219.3 1001.78   239.3  997.91   289.1   998.8     309  992.03
   348.9  989.68   358.9  986.83   388.8  986.65   438.6  980.06   458.6  972.02
   478.5  959.97   488.5  950.74   518.4  912.37   528.4  902.34   540.8  900.82
   555.8  901.35   657.6  900.66   796.8  910.16   816.7  913.36   846.5  922.31
   896.2  941.06     926  959.26   985.7  988.69  1035.4 1009.15    1105 1046.38
#Mann= 3 , 0 , 0
       0      .1       0   540.8    .045       0   555.8      .1       0
Bank Sta=540.8,555.8
XS Rating Curve= 0 ,0
Exp/Cntr=0.3,0.1

Type RM Length L Ch R = 1 ,372.1   ,176.9,174.7,172.6
XS GIS Cut Line= 3
     1823718.612      351448.914     1823603.251      351464.826
       1822820.5      351655.049
#Sta/Elev= 30
       0  990.05    19.4  983.14    29.1  976.13    67.9  958.18      97  947.76
   106.8  942.06   116.4   937.5   176.1  920.24   186.1  915.66     196   909.6
   215.9  903.46   225.8  901.15   235.8  899.68   265.6  896.63   366.6  893.15
   381.6  892.73   394.9   892.5     564  895.29   623.6  897.64   643.5  899.38
   693.3  912.98   703.2  914.94   713.1  916.22     743   919.3   762.9  919.34
   792.7  918.17   812.6  918.47   842.4  919.89   882.2   923.6     922  930.34
#Mann= 3 , 0 , 0
       0     .06       0   366.6    .045       0   381.6     .06       0
Bank Sta=366.6,381.6
XS Rating Curve= 0 ,0
Exp/Cntr=0.3,0.1

Type RM Length L Ch R = 1 ,197.2   ,187.3,197.3,207.4
XS GIS Cut Line= 2
     1823719.938      351215.539     1822895.171      351501.954
#Sta/Elev= 30
       0   926.7    29.8  918.87    39.7  913.75    49.6  909.82    89.3  898.31
    99.2   895.8   109.1  893.93   119.1  893.33   188.5   893.4     258  895.49
   297.6  896.04   327.4  895.71   347.2  895.06   386.9  892.75   416.7  894.17
   436.5  894.55   446.5  894.08   453.1  891.96   456.4   890.9   466.3  888.93
   468.1   889.2   476.2   890.4   486.2  893.28   496.1   895.3     506  895.93
   535.8  894.88   674.7  895.61   744.1  897.73   823.5  902.18   873.1  903.88
#Mann= 3 , 0 , 0
       0     .06       0   453.1    .045       0   468.1     .06       0
Bank Sta=453.1,468.1
XS Rating Curve= 0 ,0
Exp/Cntr=0.3,0.1

Chan Stop Cuts=-1
Use User Specified Reach Order=0
Composite Channel Slope=5